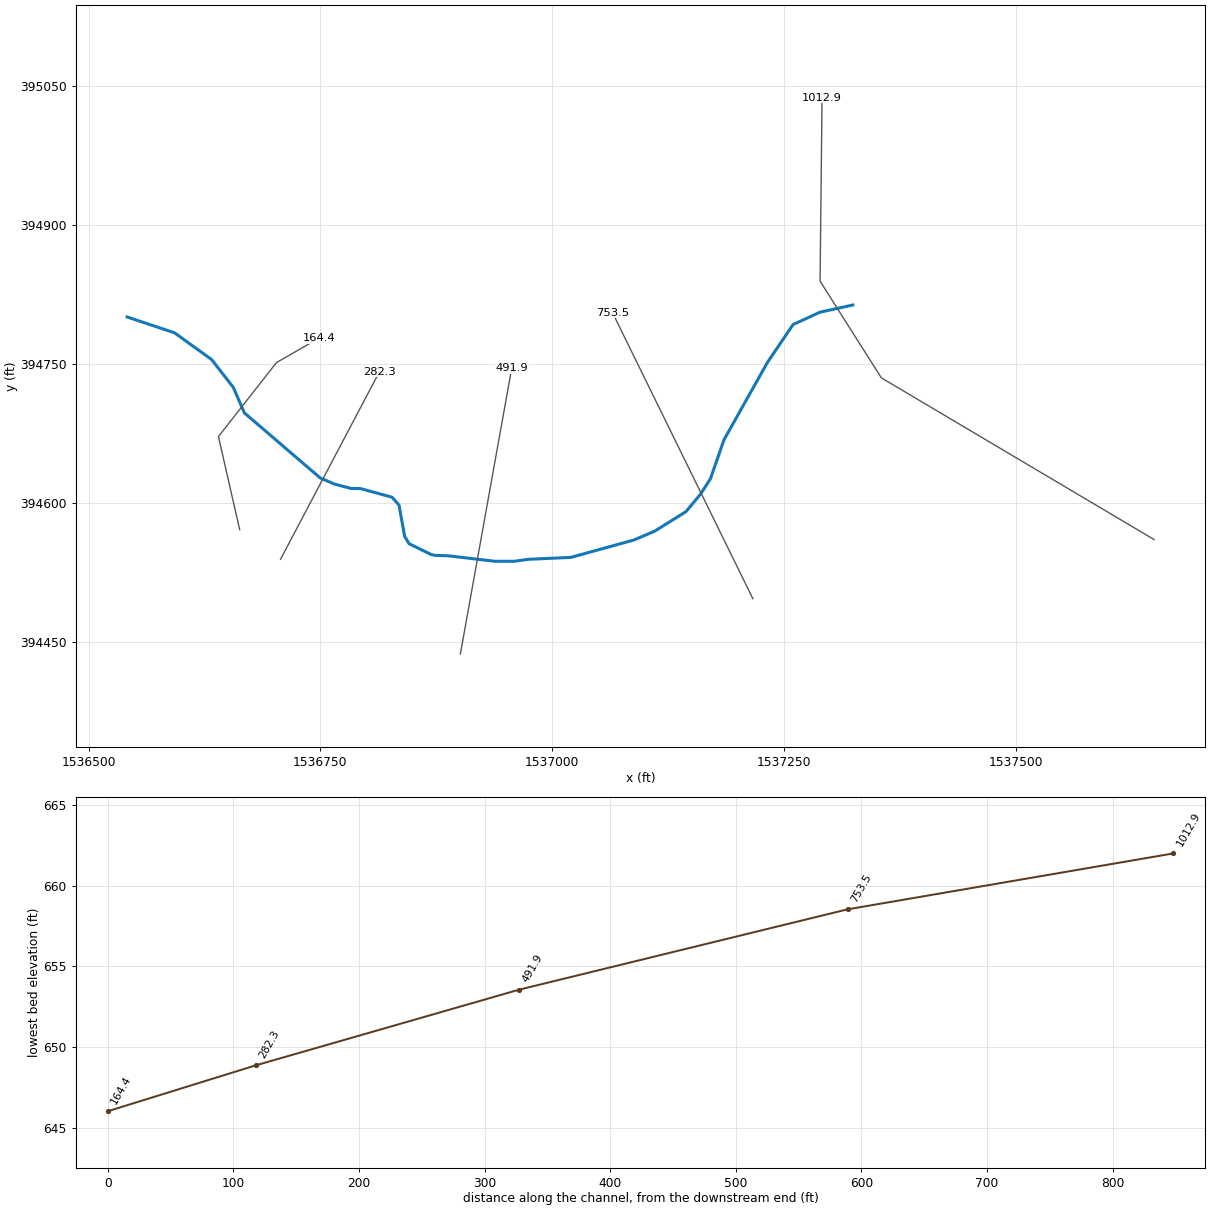
--- NP04.prj (project) ---

Proj Title=NP04
Current Plan=p01
Default Exp/Contr=0,0
English Units
Geom File=g01
Flow File=f01
Plan File=p01
BEGIN DESCRIPTION:
END DESCRIPTION:
DSS Export Rating Curves= 0
DSS Export Rating Curve Sorted= 0
DSS Export Volume Flow Curves= 0
DXF OffsetX= 0
DXF OffsetY= 0
DXF ScaleX= 0
DXF ScaleY= 0

--- NP04.p01 (plan) ---

Plan Title=Floodplain
Program Version=4.00
Geom File=g01
Flow File=f01
K Sum by GR=0
Std Step Tol=0.01
Critical Tol=0.01
Num of Std Step Trials=20
Max Error Tol=0.3
Flow Tol Ratio=0.001
Split Flow NTrial=30
Split Flow Tol=0.02
Split Flow Ratio=0.02
Log Output Level=0
Friction Slope Method=1
Unsteady Friction Slope Method=2
Unsteady Bridges Friction Slope Method=1
Global Log Level=0
CheckData=False
Run HTab=0
Run UNet=0
Run PostProcess=0
UNET Theta=0
UNET Theta Warmup=0
UNET ZTol=0
UNET ZSATol=0
UNET MxIter=0
UNET MaxInSteps=0
UNET DtIC=0
UNET DtMin=0
UNET MaxCRTS=0
UNET WFStab=0
UNET SFStab=0
UNET WFX=0
UNET SFX=0
UNET DSS MLevel=0
UNET DZMax Abort=0
UNET Convert EG Bridges=0
UNET Use Existing IB Tables=0
UNET Froude Limit=0
UNET Froude Power=0
Write IC File=0
Echo Input=False
Echo Output=False
Write Detailed=0

--- NP04.f01 (steady flow) ---

Flow Title=NFF Regression Equation
Program Version=4.00
Number of Profiles=1
Profile Names=P100yr
River Rch & RM=NP04,Main      ,1012.9
360.3189
River Rch & RM=NP04,Main      ,282.3
365.6120
Boundary for River Rch & Prof#=NP04,Main      ,1
Up Type=0
Dn Type=3
Dn Slope=0.021917

--- NP04.g01 (geometry) ---

Geom Title=Geometry
Program Version=4.00

River Reach=NP04            ,Main
Reach XY= 30
     1537324.204      394813.672     1537288.629       394805.89
     1537259.724      394792.549     1537231.931      394751.415
     1537185.239      394668.036     1537170.643      394625.966
     1537159.883      394609.228     1537144.128      394590.322
     1537110.518      394569.316     1537088.461      394559.863
      1537020.19      394540.957     1536973.976      394538.856
     1536959.271      394536.756     1536938.265      394536.756
     1536887.189      394542.736     1536874.184      394543.097
     1536869.492      394544.036     1536845.561      394555.767
     1536840.869      394563.743     1536834.769      394597.527
     1536827.262      394605.973     1536793.009      394615.358
     1536783.419      394615.358     1536765.006      394620.232
     1536749.774      394626.832     1536668.063      394697.075
     1536656.057      394724.734     1536632.711      394754.751
     1536592.688      394783.655     1536541.621      394800.751

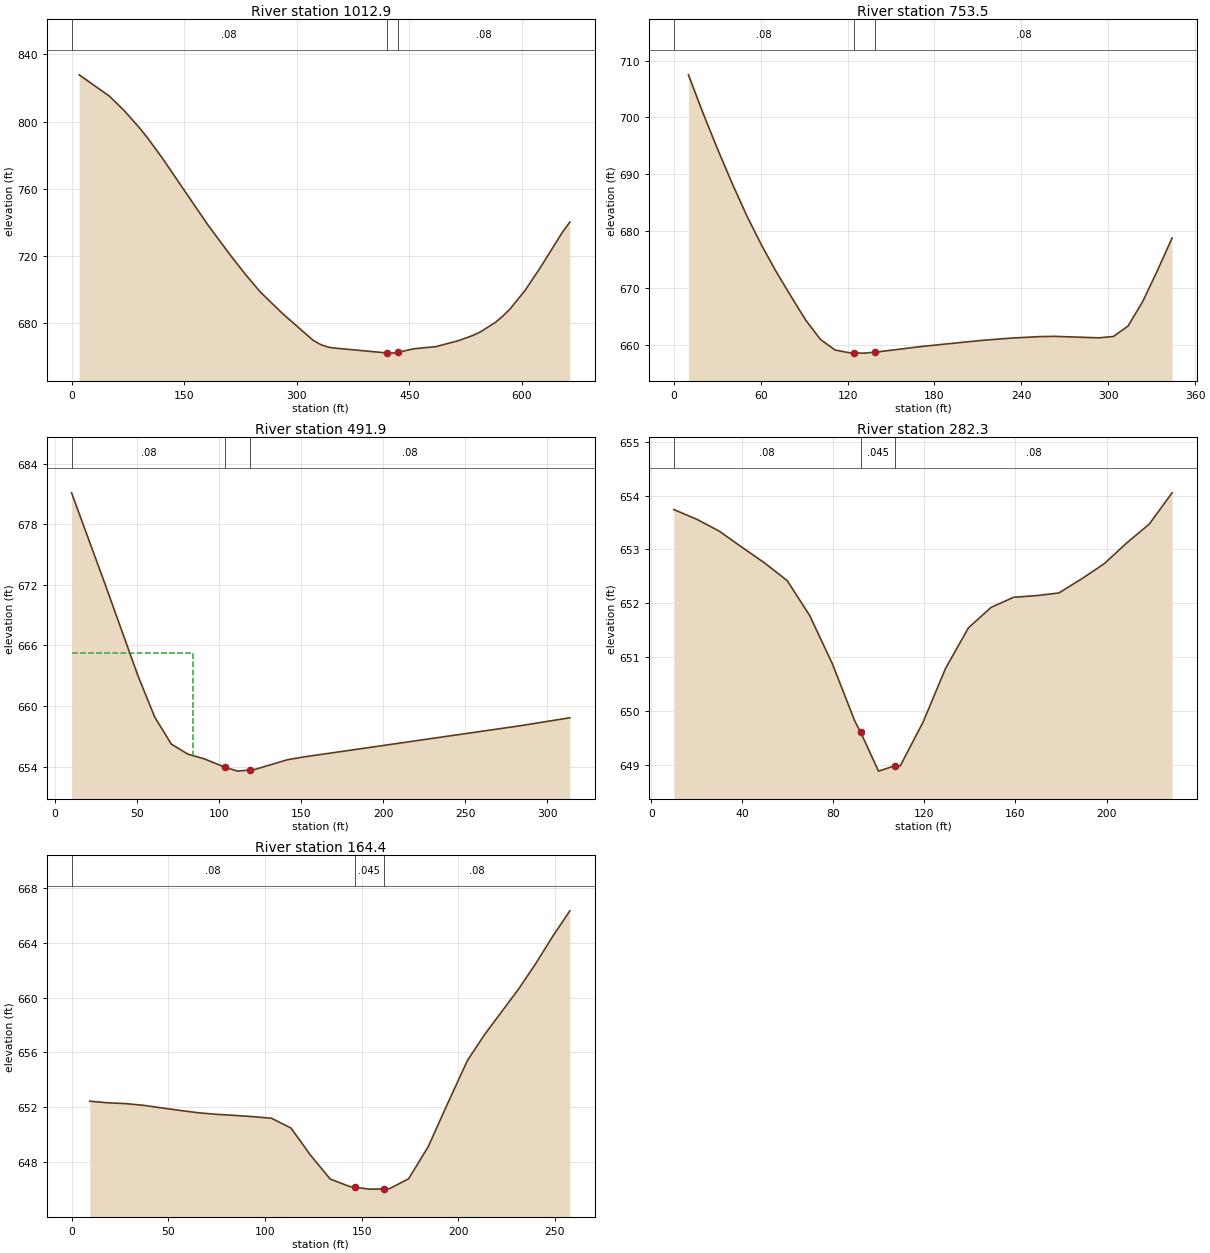
Type RM Length L Ch R = 1 ,1012.9  ,262.6,259.5,255.7
XS GIS Cut Line= 4
     1537648.996      394560.235     1537354.899      394734.989
     1537288.833      394839.415     1537290.965       395037.61
#Sta/Elev= 30
    10.1  827.84    50.3  815.17    70.4  806.39    90.6  796.18   100.6  790.63
   120.7  778.36   181.1  738.76   211.3  720.52   231.4  709.06   251.5  698.41
   281.7  685.34     322  669.58     332  667.07   342.1  665.56   351.6  664.95
   420.1   662.1   427.6  661.99   435.1  662.46   456.2  664.59   485.5  665.87
   515.2  669.38     535  672.57     545  674.69   564.8  680.33   574.7  684.06
   584.6  688.49   604.4  699.44   624.2   712.7     654  733.98   663.9  740.08
#Mann= 3 , 0 , 0
       0     .08       0   420.1    .045       0   435.1     .08       0
Bank Sta=420.1,435.1
XS Rating Curve= 0 ,0
Exp/Cntr=0.3,0.1

Type RM Length L Ch R = 1 ,753.5   ,275.2,261.5,248.5
XS GIS Cut Line= 2
     1537216.375      394496.301     1537065.064      394805.316
#Sta/Elev= 26
    10.1  707.49    20.2  700.73    30.4  694.31    40.5  688.26    50.6  682.59
    60.7  677.47    70.8  672.81      81   668.5    91.1  664.34   101.2  660.95
   111.3  659.09   121.4  658.58   124.1  658.56   131.6  658.53   139.1   658.7
     172  659.72   212.5  660.77   232.8  661.17     253  661.44   263.1  661.48
   293.5  661.22   303.6  661.46   313.7   663.3   323.8   667.6     334  673.06
   344.1  678.79
#Mann= 3 , 0 , 0
       0     .08       0   124.1    .045       0   139.1     .08       0
Bank Sta=124.1,139.1
XS Rating Curve= 0 ,0
Exp/Cntr=0.3,0.1

Type RM Length L Ch R = 1 ,491.9   ,215.9,209.6,202.6
XS GIS Cut Line= 2
     1536900.966      394436.629     1536956.376      394745.644
#Sta/Elev= 15
    10.1   681.1    30.4  672.12    50.6  662.99    60.8  658.91    70.9  656.24
      81  655.24    91.1  654.77   103.9  653.93   111.4  653.56   118.9  653.68
   121.5  653.71   141.8  654.69   151.9  654.97   283.6  658.05   313.9  658.84
#Mann= 3 , 0 , 0
    10.1     .08       0   103.9    .045       0   118.9     .08       0
#XS Ineff= 2 , 0
           83.98  665.24
Permanent Ineff=
       F       F
Bank Sta=103.9,118.9
XS Rating Curve= 0 ,0
Exp/Cntr=0.3,0.1

Type RM Length L Ch R = 1 ,282.3   ,121.3,117.9,114.8
XS GIS Cut Line= 2
     1536707.033      394538.924      1536813.59      394741.382
#Sta/Elev= 25
     9.9  653.74    19.9  653.56    29.8  653.34    39.8  653.04    49.7  652.75
    59.7  652.42    69.6  651.77    79.6  650.87    89.5   649.8      92   649.6
   99.83  648.88     107  648.98   109.4  648.98   119.4  649.79   129.3  650.79
   139.3  651.54   149.2  651.92   159.2  652.11   169.1  652.14   179.1  652.19
     189  652.45   198.9  652.73   208.9  653.12   218.8  653.47   228.8  654.05
#Mann= 3 , 0 , 0
     9.9     .08       0      92    .045       0     107     .08       0
Bank Sta=92,107
XS Rating Curve= 0 ,0
Exp/Cntr=0.3,0.1

Type RM Length L Ch R = 1 ,164.4   ,157.4,164.4,171.1
XS GIS Cut Line= 4
      1536663.01      394570.782     1536640.083      394671.521
     1536702.611      394751.417     1536748.464      394777.817
#Sta/Elev= 29
     9.4  652.45    18.8  652.33    28.2  652.27    37.6  652.14      47  651.95
    56.4  651.77    65.7   651.6    75.1  651.49    84.5  651.41    93.9  651.32
   103.3  651.21   113.5  650.49   123.6  648.51   133.8  646.77   143.9  646.23
   146.5  646.18     154  646.04   161.5  646.05   164.2  646.06   174.3  646.79
   184.5  649.14   194.6  652.31   204.8  655.43   213.6   657.3   222.4  658.96
   231.2  660.62     240  662.46   248.9  664.47   257.7  666.32
#Mann= 3 , 0 , 0
       0     .08       0   146.5    .045       0   161.5     .08       0
Bank Sta=146.5,161.5
XS Rating Curve= 0 ,0
Exp/Cntr=0.3,0.1

Chan Stop Cuts=-1
Use User Specified Reach Order=0